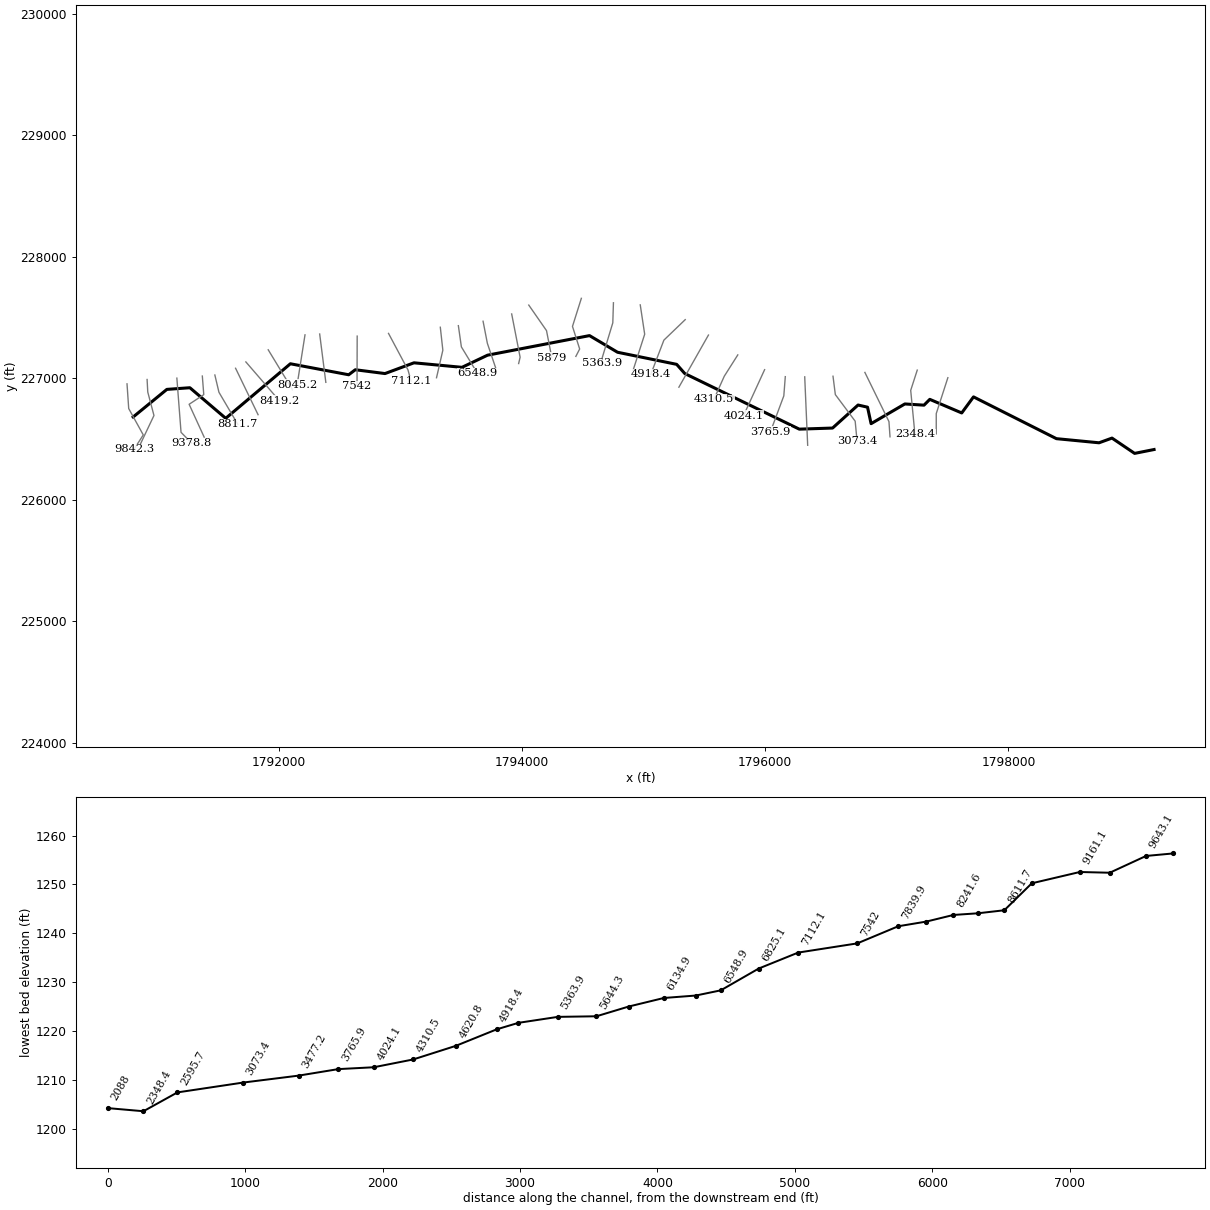
--- INDIANFKCK.prj (project) ---

Proj Title=INDIANFKCK
Current Plan=p01
Default Exp/Contr=0,0
English Units
Geom File=g01
Flow File=f01
Plan File=p01
BEGIN DESCRIPTION:
END DESCRIPTION:
DSS Export Rating Curves= 0
DSS Export Rating Curve Sorted= 0
DSS Export Volume Flow Curves= 0
DXF OffsetX= 0
DXF OffsetY= 0
DXF ScaleX= 0
DXF ScaleY= 0

--- INDIANFKCK.p01 (plan) ---

Plan Title=Floodplain
Program Version=4.00
Geom File=g01
Flow File=f01
K Sum by GR=0
Std Step Tol=0.01
Critical Tol=0.01
Num of Std Step Trials=20
Max Error Tol=0.3
Flow Tol Ratio=0.001
Split Flow NTrial=30
Split Flow Tol=0.02
Split Flow Ratio=0.02
Log Output Level=0
Friction Slope Method=1
Unsteady Friction Slope Method=2
Unsteady Bridges Friction Slope Method=1
Global Log Level=0
CheckData=False
Run HTab=0
Run UNet=0
Run PostProcess=0
UNET Theta=0
UNET Theta Warmup=0
UNET ZTol=0
UNET ZSATol=0
UNET MxIter=0
UNET MaxInSteps=0
UNET DtIC=0
UNET DtMin=0
UNET MaxCRTS=0
UNET WFStab=0
UNET SFStab=0
UNET WFX=0
UNET SFX=0
UNET DSS MLevel=0
UNET DZMax Abort=0
UNET Convert EG Bridges=0
UNET Use Existing IB Tables=0
UNET Froude Limit=0
UNET Froude Power=0
Write IC File=0
Echo Input=False
Echo Output=False
Write Detailed=0

--- INDIANFKCK.f01 (steady flow) ---

Flow Title=NFF Regression Equation
Program Version=4.10
Number of Profiles= 1
Profile Names=P100yr
River Rch & RM=INDIANFKCK,Main            ,9842.3
872.1114
River Rch & RM=INDIANFKCK,Main            ,9378.8
959.2003
River Rch & RM=INDIANFKCK,Main            ,8241.6
978.9599
River Rch & RM=INDIANFKCK,Main            ,8045.2
1268.996
River Rch & RM=INDIANFKCK,Main            ,5644.3
1351.726
River Rch & RM=INDIANFKCK,Main            ,385.4
1490.469
River Rch & RM=INDIANFKCK,Main            ,95.5
 1496.62
Boundary for River Rch & Prof#=INDIANFKCK,Main            , 1
Up Type= 0
Dn Type= 3
Dn Slope=0.00499
DSS Import GetInterval= 0
DSS Import GetPeak= 0
DSS Import FillOption= 0

--- INDIANFKCK.g01 (geometry) ---

Geom Title=USGS 10m DEM
Program Version=5.03

River Reach=INDIANFKCK      ,Main
Reach XY= 30
     1790802.662      226681.921     1791079.739      226908.811
     1791268.988      226922.403      1791563.84      226670.943
     1792095.514      227119.494      1792574.91      227029.052
      1792629.28      227070.352     1792873.422      227038.985
     1793111.813      227127.336     1793506.517      227090.218
     1793716.677       227190.07     1794555.228      227351.089
     1794785.777      227214.118     1795271.985      227114.707
      1795338.54      227039.127     1796280.262      226581.811
     1796553.955      226590.837     1796763.481      226780.205
     1796841.376       226762.43     1796870.713      226626.933
      1797148.23      226788.983     1797305.803      226779.098
     1797353.353      226826.808     1797616.009      226715.008
     1797712.862      226847.122     1798394.678      226503.518
     1798745.231      226469.637      1798851.67      226508.248
     1799037.669      226382.492     1799197.583      226414.262

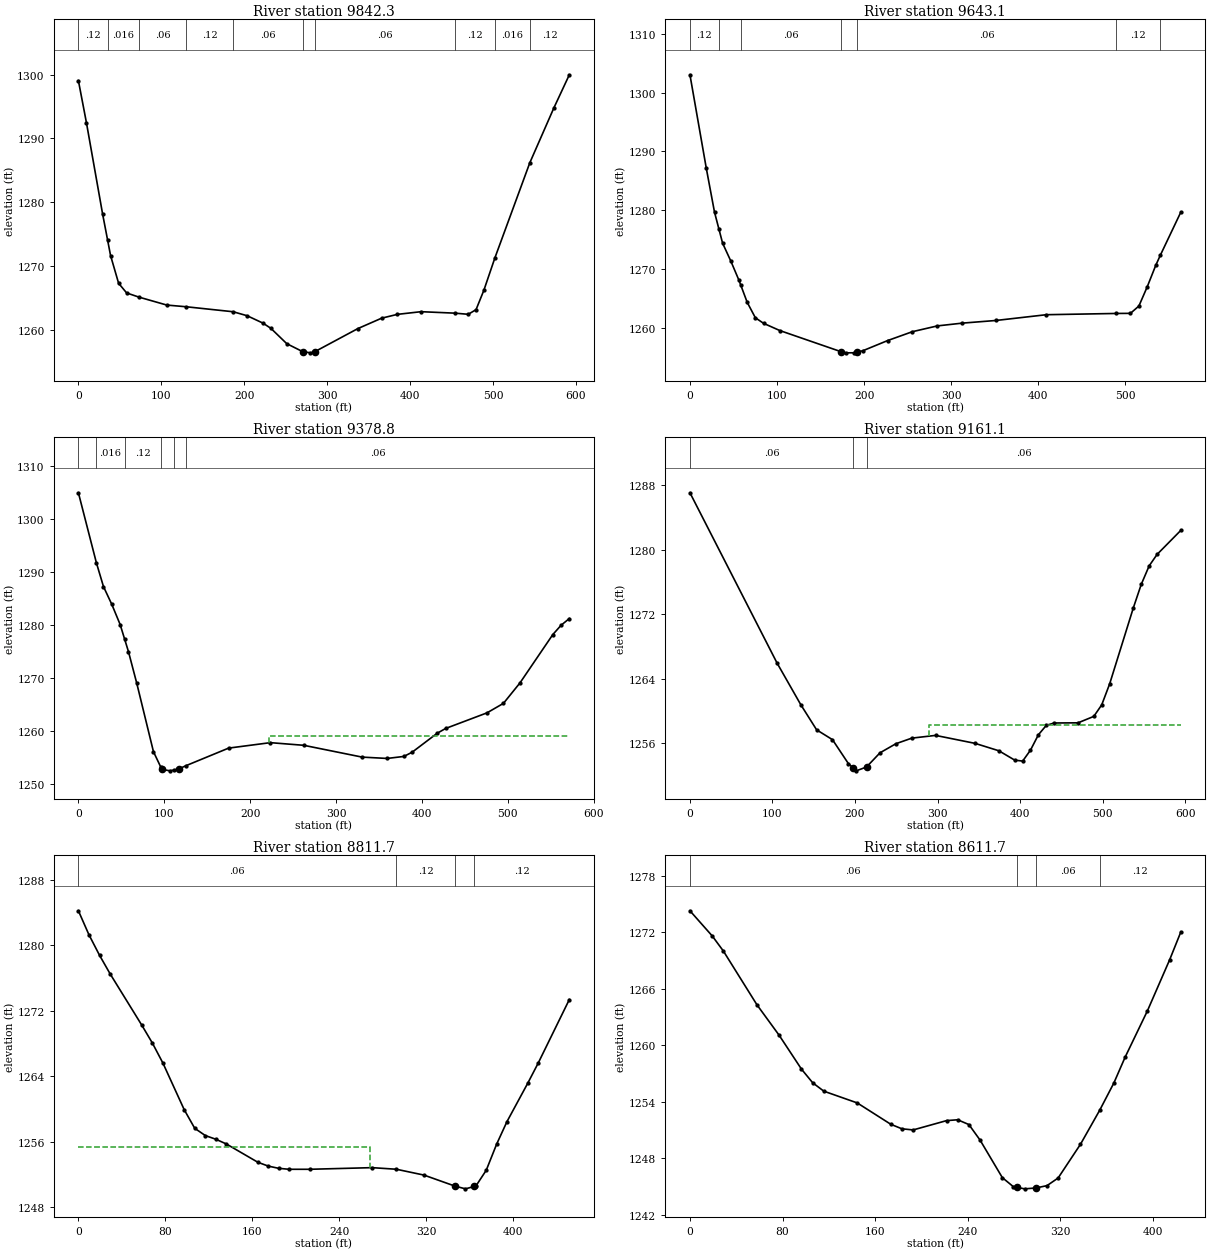
Type RM Length L Ch R = 1 ,9842.3  ,204.7,199.2,188.9
XS GIS Cut Line= 4
     1790752.115      226954.347     1790766.004      226751.222
     1790885.796      226534.209     1790809.407      226416.153
#Sta/Elev= 30
       0 1299.08     9.7 1292.47    29.1 1278.21    35.31273.998    38.8 1271.62
    48.5 1267.27    58.2 1265.75   72.991265.099   106.6 1263.85  129.811263.586
  186.741262.799   203.6 1262.17   222.7 1261.01   232.2 1260.19   251.3 1257.79
   270.3 1256.55   279.9 1256.35  285.161256.533   337.1 1260.16   365.7 1261.79
   384.7 1262.39   413.3 1262.81  454.141262.579   470.2  1262.4   479.6 1263.13
     489 1266.16  502.391271.279  544.411286.175   573.4 1294.78   592.1    1300
#Mann= 10 ,-1 , 0
       0     .12       0    35.3    .016       0   72.99     .06       0
  129.81     .12       0  186.74     .06       0   270.3    .045       0
  285.16     .06       0  454.14     .12       0  502.39    .016       0
  544.41     .12       0
Bank Sta=270.3,285.16
XS Rating Curve= 0 ,0
Exp/Cntr=0.3,0.1

Type RM Length L Ch R = 1 ,9643.1  ,268,264.3,262.7
XS GIS Cut Line= 4
     1790917.263      226990.227     1790922.688      226887.146
     1790973.686      226694.003     1790861.924      226458.543
#Sta/Elev= 30
       0 1303.01    18.8 1287.12    28.2  1279.7    33.11276.923    37.5 1274.43
    46.9 1271.41    56.3 1268.13   58.481267.267    65.7 1264.41    75.1 1261.78
    84.5 1260.84   103.2 1259.61  173.321256.031   179.3 1255.83   188.8 1255.84
  192.271255.963   198.4 1256.18   226.9 1257.91   255.4 1259.42     284  1260.4
   312.6 1260.87   351.2 1261.32   409.2  1262.3  489.681262.513   505.7 1262.53
   515.4 1263.77     525 1267.04   534.7 1270.65  539.951272.367   563.6 1279.72
#Mann= 7 ,-1 , 0
       0     .12       0    33.1    .016       0   58.48     .06       0
  173.32    .045       0  192.27     .06       0  489.68     .12       0
  539.95    .016       0
Bank Sta=173.32,192.27
XS Rating Curve= 0 ,0
Exp/Cntr=0.3,0.1

Type RM Length L Ch R = 1 ,9378.8  ,240.9,217.7,192.1
XS GIS Cut Line= 3
      1791162.01      227001.431     1791196.343      226555.765
     1791283.538      226466.709
#Sta/Elev= 30
       0 1304.89   20.991291.645    29.2 1287.18    38.9 1283.82    48.6 1280.02
   53.831277.259    58.3  1274.9      68  1268.9    87.4 1256.01      961253.078
    97.2 1252.67   106.9  1252.4     1111252.547   116.6 1252.74  125.421253.385
   174.9 1256.69   223.5 1257.72   262.4 1257.22   330.4 1254.99   359.5 1254.74
     379 1255.12   388.7 1255.93   417.8  1259.5   427.6  1260.4   475.8 1263.35
   494.9 1265.14   514.1 1268.99   552.4 1278.13     562 1279.88   571.6 1281.15
#Mann= 6 ,-1 , 0
       0     .12       0   20.99    .016       0   53.83     .12       0
      96    .045       0     111     .12       0  125.42     .06       0
#XS Ineff= 2 , 0
                          222.04         1259.05
Permanent Ineff=
       F       F
Bank Sta=97.2,116.6
XS Rating Curve= 0 ,0
Exp/Cntr=0.3,0.1

Type RM Length L Ch R = 1 ,9161.1  ,314.8,349.4,383.8
XS GIS Cut Line= 4
     1791371.364      227018.439       1791383.3      226865.444
     1791262.857      226786.234     1791386.555      226516.052
#Sta/Elev= 30
       0 1287.07   105.5 1265.94   134.3 1260.76   153.5 1257.64   172.7 1256.42
   191.9 1253.46  197.671252.914   201.5 1252.55  213.921253.027   230.3 1254.79
   249.6 1255.92   268.8 1256.61   297.6 1256.95   345.5 1255.96   374.3 1255.04
   393.5 1253.88   403.1 1253.76   412.6 1255.12   422.2 1257.03   431.8  1258.2
   441.4 1258.49   470.2 1258.51   489.3 1259.31   498.9 1260.74   508.5 1263.34
   537.2 1272.78   546.8  1275.7   556.4    1278     566 1279.42   594.8 1282.41
#Mann= 3 ,-1 , 0
       0     .06       0  197.67    .045       0  213.92     .06       0
#XS Ineff= 2 , 0
                          289.14         1258.18
Permanent Ineff=
       F       F
Bank Sta=197.67,213.92
XS Rating Curve= 0 ,0
Exp/Cntr=0.3,0.1

Type RM Length L Ch R = 1 ,8811.7  ,201.5,199.9,197.4
XS GIS Cut Line= 3
     1791474.446      227027.119     1791508.083      226884.975
     1791663.248      226621.304
#Sta/Elev= 30
       0 1284.23     9.7  1281.3    19.5 1278.78    29.2 1276.52    58.4 1270.24
    68.2 1268.04    77.9 1265.59    97.4 1259.92   107.1 1257.64   116.9 1256.75
   126.6  1256.3   136.3 1255.72   165.2 1253.49   174.8 1253.02   184.3 1252.75
   193.9 1252.63     213 1252.63   270.4 1252.83  292.711252.636   318.2 1251.92
   346.8 1250.57   356.4 1250.24  364.341250.529     366 1250.59   375.5 1252.51
   385.1 1255.71   394.6 1258.46   413.8 1263.17   423.3  1265.6     452 1273.38
#Mann= 4 ,-1 , 0
       0     .06       0  292.71     .12       0   346.8    .045       0
  364.34     .12       0
#XS Ineff= 2 , 0
          268.91 1255.31
Permanent Ineff=
       F       F
Bank Sta=346.8,364.34
XS Rating Curve= 0 ,0
Exp/Cntr=0.3,0.1

Type RM Length L Ch R = 1 ,8611.7  ,184.9,192.5,197.9
XS GIS Cut Line= 2
     1791644.779      227082.594     1791829.698      226700.731
#Sta/Elev= 30
       0 1274.28    19.3  1271.6    28.9    1270    57.9 1264.29    77.1 1261.05
    96.4 1257.45   106.1    1256   115.7 1255.11   144.6 1253.86   173.6 1251.59
   183.2 1251.11   192.9 1250.99   221.8 1251.98   231.4 1252.07   241.1 1251.56
   250.7 1249.92     270 1245.92   279.6 1244.95  282.441244.885   289.3 1244.73
   298.9 1244.82   308.6 1245.07   318.2 1245.88   337.5 1249.46  354.211253.097
   366.4 1255.98   376.1 1258.72   395.4 1263.65   414.6 1269.07   424.3 1272.04
#Mann= 4 ,-1 , 0
       0     .06       0  282.44    .045       0   298.9     .06       0
  354.21     .12       0
Bank Sta=282.44,298.9
XS Rating Curve= 0 ,0
Exp/Cntr=0.3,0.1

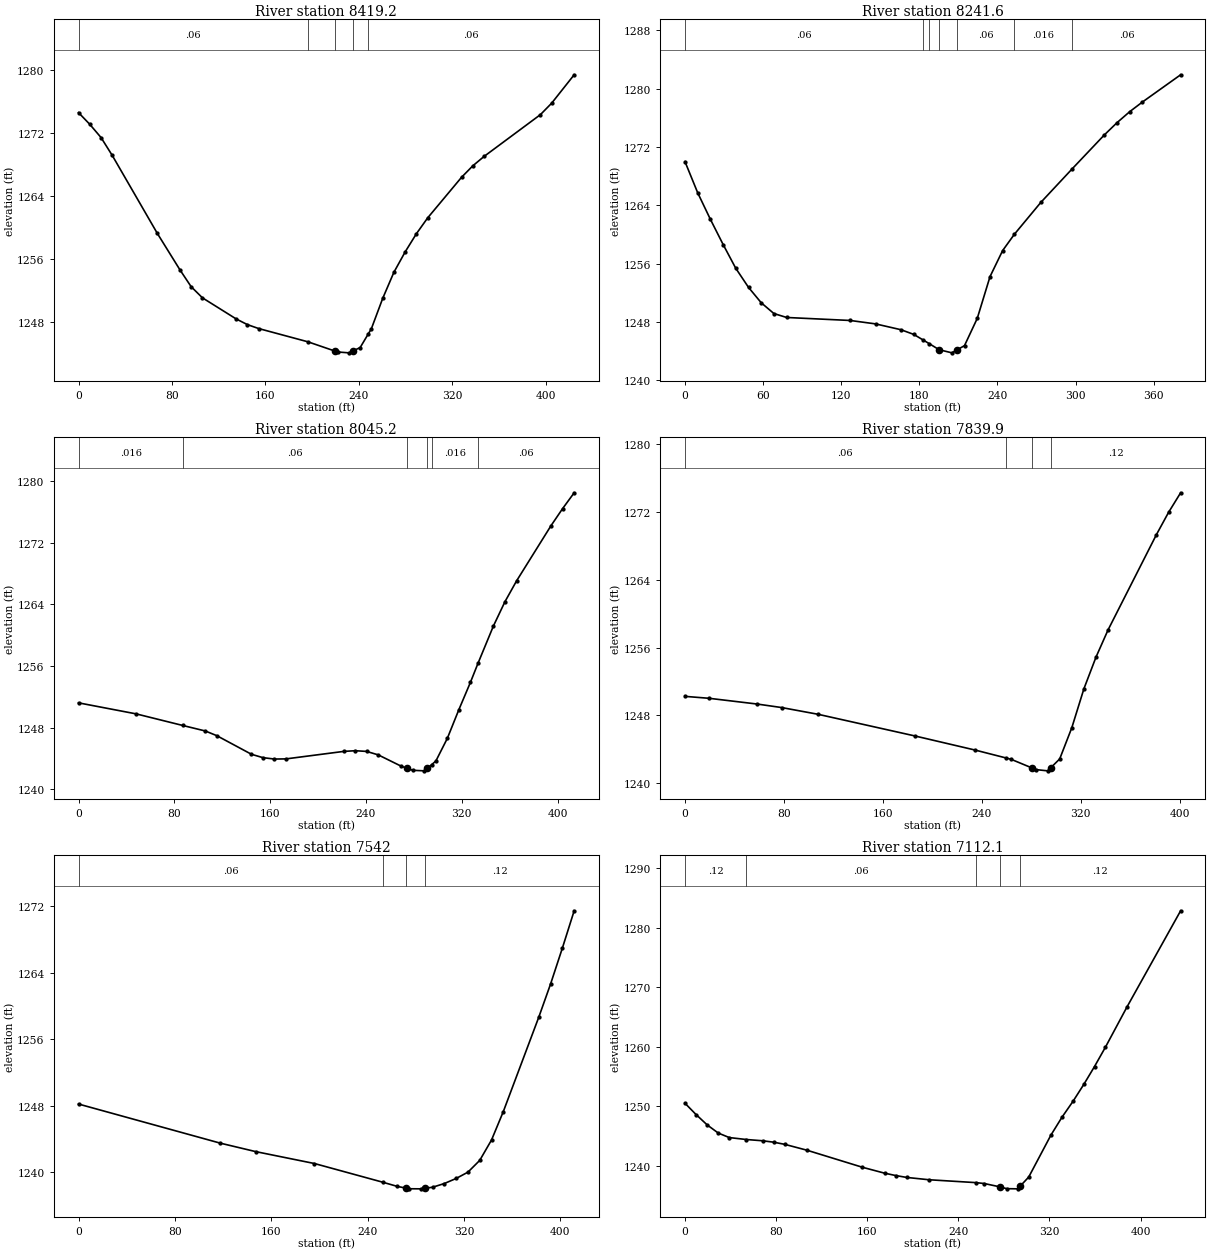
Type RM Length L Ch R = 1 ,8419.2  ,181,177.6,173.7
XS GIS Cut Line= 2
     1791729.415      227134.677     1792006.781      226813.578
#Sta/Elev= 30
       0  1274.6     9.6 1273.12    19.3 1271.43    28.9 1269.16    67.5 1259.26
    86.8 1254.65    96.4 1252.51   106.1 1251.09     135 1248.41   144.6 1247.69
   154.3 1247.19  196.461245.507  219.171244.351   221.8 1244.22   231.4 1244.11
  234.651244.335   241.1 1244.78  248.181246.543   250.7 1247.17   260.4 1251.02
     270 1254.34   279.7 1256.94   289.3 1259.24   298.9 1261.24   327.9 1266.39
   337.5 1267.84   347.2 1269.04   395.4 1274.34     405 1275.79   424.3  1279.4
#Mann= 5 ,-1 , 0
       0     .06       0  196.46     .12       0  219.17    .045       0
  234.65     .12       0  248.18     .06       0
Bank Sta=219.17,234.65
XS Rating Curve= 0 ,0
Exp/Cntr=0.3,0.1

Type RM Length L Ch R = 1 ,8241.6  ,212.7,196.4,177.6
XS GIS Cut Line= 2
     1791913.207      227234.356     1792110.948      226909.064
#Sta/Elev= 30
       0    1270     9.8 1265.71    19.5 1262.09    29.3 1258.63      39 1255.37
    48.8 1252.75    58.6 1250.63    68.3 1249.16    78.1 1248.62   126.9 1248.21
   146.4 1247.74   165.9 1246.94   175.7  1246.3   183.11245.515  187.751245.014
   195.2  1244.2     205 1243.77   209.2  1244.2   214.7 1244.76   224.5  1248.5
   234.3 1254.23     244  1257.8  253.061260.047   273.3  1264.4   297.41269.008
   322.1 1273.66   331.9 1275.35   341.6 1276.85   351.4 1278.18   380.7 1281.91
#Mann= 7 ,-1 , 0
       0     .06       0   183.1     .12       0  187.75     .06       0
   195.2    .045       0   209.2     .06       0  253.06    .016       0
   297.4     .06       0
Bank Sta=195.2,209.2
XS Rating Curve= 0 ,0
Exp/Cntr=0.3,0.1

Type RM Length L Ch R = 1 ,8045.2  ,198.9,205.3,211.7
XS GIS Cut Line= 2
     1792215.699      227357.334      1792151.29      226948.479
#Sta/Elev= 30
       0 1251.24    48.1 1249.81    87.11248.303   105.9 1247.59   115.5 1246.98
   144.4 1244.57     154 1244.13   163.6 1243.95   173.3 1243.97   221.4 1244.94
     231 1245.03   240.6 1244.94   250.3 1244.49   269.5 1243.02  274.341242.753
   279.1 1242.49   288.8 1242.42  291.411242.763  294.811243.211   298.4 1243.69
     308 1246.64   317.6 1250.35   327.3 1253.91  333.571256.359   346.5 1261.22
   356.1 1264.36   365.8 1267.06   394.6 1274.23   404.3 1276.45   413.9 1278.49
#Mann= 6 ,-1 , 0
       0    .016       0    87.1     .06       0  274.34    .045       0
  291.41     .06       0  294.81    .016       0  333.57     .06       0
Bank Sta=274.34,291.41
XS Rating Curve= 0 ,0
Exp/Cntr=0.3,0.1

Type RM Length L Ch R = 1 ,7839.9  ,300.2,297.9,294.3
XS GIS Cut Line= 2
     1792336.359      227364.278     1792386.967      226966.709
#Sta/Elev= 21
       0 1250.24    19.6 1250.01    58.6 1249.33    78.2 1248.92   107.5 1248.13
   185.7 1245.58   234.6 1243.91  259.231242.993   263.9 1242.81   280.6  1241.8
   283.5 1241.61   293.2 1241.46   295.6  1241.8     303 1242.86   312.8 1246.54
   322.6 1251.14   332.4 1254.88   342.1 1258.07   381.2  1269.3     391 1271.92
   400.8 1274.24
#Mann= 4 ,-1 , 0
       0     .06       0  259.23     .12       0   280.6    .045       0
   295.6     .12       0
Bank Sta=280.6,295.6
XS Rating Curve= 0 ,0
Exp/Cntr=0.3,0.1

Type RM Length L Ch R = 1 ,7542    ,416.4,429.9,440.7
XS GIS Cut Line= 2
     1792644.779      227346.917     1792643.477      226935.459
#Sta/Elev= 21
       0 1248.18   117.6 1243.47     147 1242.45   195.9 1241.01  252.521238.761
   264.5 1238.26   271.81238.047   274.3 1237.97   284.1 1237.96  288.041238.039
   293.9 1238.15   303.7  1238.6   313.5 1239.21   323.3 1239.97   333.1 1241.39
   342.9 1243.85   352.7 1247.28   382.1 1258.64   391.9 1262.64   401.7 1266.97
   411.5 1271.47
#Mann= 4 ,-1 , 0
       0     .06       0  252.52     .12       0   271.8    .045       0
  288.04     .12       0
Bank Sta=271.8,288.04
XS Rating Curve= 0 ,0
Exp/Cntr=0.3,0.1

Type RM Length L Ch R = 1 ,7112.1  ,302.8,287,270.4
XS GIS Cut Line= 3
     1792902.592      227369.052     1793062.748      227068.271
     1793087.488      226977.125
#Sta/Elev= 30
       0 1250.49     9.7 1248.59    19.5 1246.84    29.2 1245.47    38.9 1244.71
   53.931244.381    68.2 1244.17    77.9 1243.93    87.6 1243.57   107.1 1242.58
   155.8 1239.71   175.2 1238.72     185 1238.32   194.7    1238   214.2 1237.61
  255.791237.122   262.9 1236.97  276.881236.398   282.4 1236.11   292.1 1236.08
   294.1 1236.49   301.8 1238.06   321.3 1245.12     331 1248.13   340.8 1250.84
   350.2 1253.66   359.6 1256.67   369.1  1259.9     388 1266.66   435.2 1282.88
#Mann= 5 ,-1 , 0
       0     .12       0   53.93     .06       0  255.79     .12       0
  276.88    .045       0   294.1     .12       0
Bank Sta=276.88,294.1
XS Rating Curve= 0 ,0
Exp/Cntr=0.3,0.1

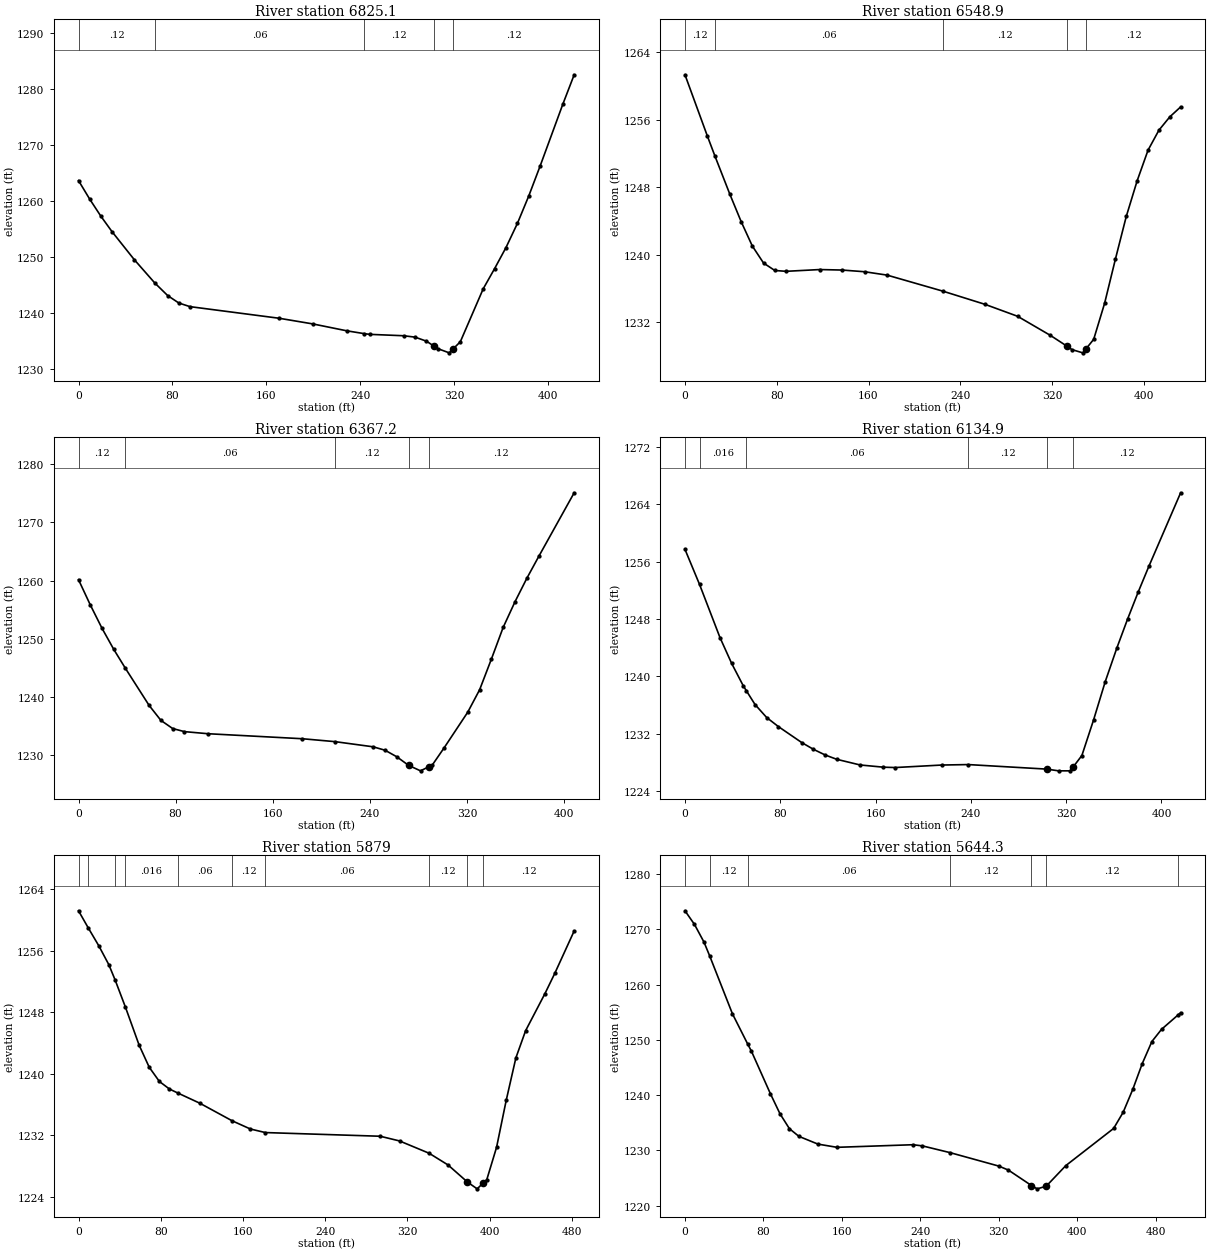
Type RM Length L Ch R = 1 ,6825.1  ,258,276.3,293
XS GIS Cut Line= 3
     1793328.373      227419.834     1793349.206      227231.032
     1793297.123      227004.469
#Sta/Elev= 30
       0 1263.66     9.5 1260.35      19  1257.3    28.5 1254.53    47.5 1249.51
   64.941245.341      76 1243.07    85.5 1241.74      95 1241.09     171 1239.01
   199.6    1238   228.7 1236.76  243.331236.263   248.1 1236.13   277.1 1235.88
   286.8 1235.63   296.5 1234.91  303.281233.973   306.2 1233.57   315.9 1232.82
  319.361233.545   325.4 1234.81   344.9 1244.29   354.6  1247.9   364.3 1251.67
     374 1255.98   383.7  1260.9   393.4 1266.27   412.7 1277.31   422.4  1282.6
#Mann= 5 ,-1 , 0
       0     .12       0   64.94     .06       0  243.33     .12       0
  303.28    .045       0  319.36     .12       0
Bank Sta=303.28,319.36
XS Rating Curve= 0 ,0
Exp/Cntr=0.3,0.1

Type RM Length L Ch R = 1 ,6548.9  ,186.8,181.7,177.2
XS GIS Cut Line= 3
      1793476.81      227432.854      1793501.55      227258.375
     1793634.363      227039.625
#Sta/Elev= 30
       0 1261.31    19.6 1254.02   26.221251.642    39.2 1247.13      49  1243.9
    58.7 1241.02    68.5    1239    78.3 1238.12    88.1 1238.02   117.5 1238.23
   137.1 1238.17   156.6 1237.97   176.2 1237.57  224.961235.664   261.5 1234.11
     290 1232.69   318.4 1230.44  333.421229.113   337.4 1228.74   346.8 1228.36
  349.851228.874   356.3 1229.96   365.8 1234.22   375.3  1239.5   384.7 1244.52
   394.2 1248.75   403.7 1252.38   413.2 1254.75   422.7 1256.33   432.1  1257.5
#Mann= 5 ,-1 , 0
       0     .12       0   26.22     .06       0  224.96     .12       0
  333.42    .045       0  349.85     .12       0
Bank Sta=333.42,349.85
XS Rating Curve= 0 ,0
Exp/Cntr=0.3,0.1

Type RM Length L Ch R = 1 ,6367.2  ,234.9,232.2,228.7
XS GIS Cut Line= 3
     1793679.935      227469.313     1793715.092      227288.323
     1793786.706      227076.084
#Sta/Elev= 28
       0 1260.16     9.7 1255.83    19.4 1251.79    29.1 1248.16   38.561244.951
    58.2 1238.54    67.9 1235.97    77.6 1234.57    87.3 1234.04   106.7 1233.68
   184.4 1232.82  211.471232.316   242.8 1231.43   252.6 1230.84   262.3 1229.71
     272 1228.24   281.8  1227.3  288.471227.988   291.5  1228.3   301.2 1231.24
   320.7 1237.38   330.5 1241.24   340.2 1246.51   349.9 1251.96   359.7 1256.39
   369.4  1260.4   379.2 1264.15   408.4  1275.1
#Mann= 5 ,-1 , 0
       0     .12       0   38.56     .06       0  211.47     .12       0
     272    .045       0  288.47     .12       0
Bank Sta=272,288.47
XS Rating Curve= 0 ,0
Exp/Cntr=0.3,0.1

Type RM Length L Ch R = 1 ,6134.9  ,255.5,255.9,255.4
XS GIS Cut Line= 3
     1793915.178      227529.209     1793984.623      227173.306
      1793972.47      227121.222
#Sta/Elev= 30
       0 1257.72   12.231252.824    29.4  1245.4    39.2 1241.79      49 1238.65
   51.571237.971    58.8 1236.06    68.6 1234.24    78.4 1232.98      98 1230.75
   107.8 1229.81   117.6 1229.02   127.4 1228.41     147 1227.62   166.6 1227.31
   176.4 1227.26   215.6 1227.61  237.791227.675   303.8 1227.04   313.6  1226.8
   323.4  1226.8  325.69  1227.3   333.2 1228.94     343  1233.9   352.8 1239.25
   362.6 1243.97   371.5 1247.96   380.4 1251.73   389.4 1255.34   416.1 1265.62
#Mann= 6 ,-1 , 0
       0     .12       0   12.23    .016       0   51.57     .06       0
  237.79     .12       0   303.8    .045       0  325.69     .12       0
Bank Sta=303.8,325.69
XS Rating Curve= 0 ,0
Exp/Cntr=0.3,0.1

Type RM Length L Ch R = 1 ,5879    ,231.7,234.7,236.6
XS GIS Cut Line= 3
     1794055.803      227602.125     1794201.637      227392.056
      1794245.04      227169.834
#Sta/Elev= 30
       0 1261.16    9.281258.982    19.7 1256.62    29.5 1254.16   35.621252.174
   45.661248.642      59  1243.7    68.8 1240.84    78.7 1238.99    88.5 1238.01
   96.461237.503     118 1236.17  149.321233.896   167.2 1232.82  181.791232.358
   293.5 1231.88   312.3 1231.27  341.091229.672   359.5 1228.15   378.4 1225.93
   387.8 1225.05   393.4 1225.76   397.2 1226.25   406.7 1230.44   416.1 1236.55
   425.5 1242.06     435  1245.6   453.8 1250.41   463.3 1253.02   482.2 1258.54
#Mann= 10 ,-1 , 0
       0    .016       0    9.28     .12       0   35.62     .06       0
   45.66    .016       0   96.46     .06       0  149.32     .12       0
  181.79     .06       0  341.09     .12       0   378.4    .045       0
   393.4     .12       0
Bank Sta=378.4,393.4
XS Rating Curve= 0 ,0
Exp/Cntr=0.3,0.1

Type RM Length L Ch R = 1 ,5644.3  ,293.5,280.4,265.9
XS GIS Cut Line= 4
     1794488.095      227657.681     1794415.178      227426.778
     1794474.206      227241.014     1794442.956       227180.25
#Sta/Elev= 30
       0 1273.36     9.7 1270.89    19.4 1267.69   25.311265.143    48.4 1254.72
   64.131249.188    67.8 1247.94    87.2 1240.23    96.9 1236.63   106.5 1233.94
   116.2 1232.55   135.6 1231.15     155 1230.57   232.5 1231.04   242.1 1230.83
  270.471229.601   320.1 1227.17   329.8 1226.45   353.3 1223.66   359.1 1223.06
   368.3 1223.53   388.3 1227.26   437.1 1233.99   446.8 1236.91   456.6 1241.05
   466.3 1245.73   476.1 1249.71   485.9 1251.91  503.171254.576   505.4 1254.91
#Mann= 7 ,-1 , 0
       0    .016       0   25.31     .12       0   64.13     .06       0
  270.47     .12       0   353.3    .045       0   368.3     .12       0
  503.17    .016       0
Bank Sta=353.3,368.3
XS Rating Curve= 0 ,0
Exp/Cntr=0.3,0.1

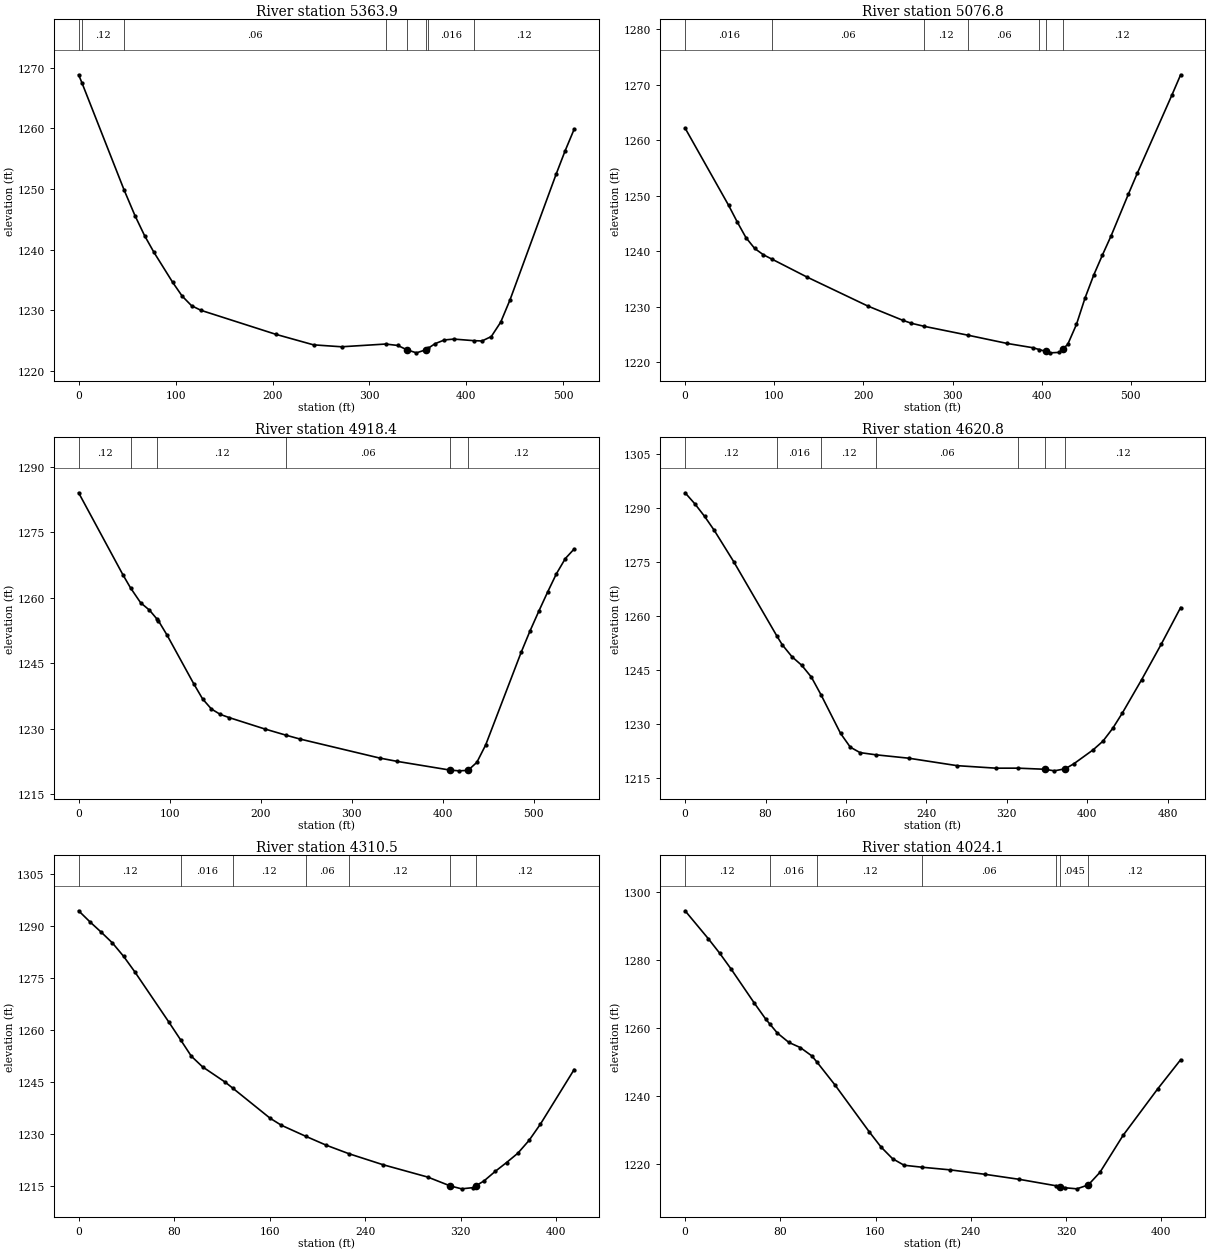
Type RM Length L Ch R = 1 ,5363.9  ,286.8,287.1,286.5
XS GIS Cut Line= 4
     1794751.984      227621.222     1794746.776      227456.292
      1794659.97      227169.834     1794658.234      227122.959
#Sta/Elev= 30
       0 1268.85    3.531267.474   46.891249.837    58.2 1245.57      68  1242.3
    77.6 1239.56    97.1 1234.56   106.8 1232.31   116.5 1230.72   126.2 1229.96
   203.6 1225.99   242.3 1224.26   271.2 1223.94  316.661224.392   329.2 1224.16
   338.8 1223.43   348.5 1222.94   358.1 1223.44   360.31223.671   367.8 1224.46
   377.4 1225.07   387.1 1225.21  407.481224.953   416.1  1224.9   425.7 1225.63
   435.4    1228     445 1231.68   492.5  1252.4   501.9 1256.31   511.2 1259.87
#Mann= 8 ,-1 , 0
       0    .016       0    3.53     .12       0   46.89     .06       0
  316.66     .12       0   338.8    .045       0   358.1     .12       0
   360.3    .016       0  407.48     .12       0
Bank Sta=338.8,358.1
XS Rating Curve= 0 ,0
Exp/Cntr=0.3,0.1

Type RM Length L Ch R = 1 ,5076.8  ,159.4,158.3,156.4
XS GIS Cut Line= 3
      1794972.47      227603.861     1795008.928      227362.542
     1794913.442      227065.667
#Sta/Elev= 30
       0 1262.21    48.8  1248.3    58.6 1245.27    68.3 1242.47    78.1 1240.52
    87.9 1239.38   97.841238.571   136.7 1235.38     205 1230.15   244.1 1227.59
   253.8 1227.05  268.241226.497  317.711224.885     361 1223.42   390.2 1222.64
  397.461222.307  404.551221.969   409.7 1221.72   419.5  1221.8  424.221222.497
   429.2 1223.23     439 1226.83   448.7 1231.62   458.5 1235.77   468.2 1239.36
     478 1242.84   497.4 1250.36   507.2 1254.05   546.2  1268.2   555.9 1271.82
#Mann= 7 ,-1 , 0
       0    .016       0   97.84     .06       0  268.24     .12       0
  317.71     .06       0  397.46     .12       0  404.55    .045       0
  424.22     .12       0
Bank Sta=404.55,424.22
XS Rating Curve= 0 ,0
Exp/Cntr=0.3,0.1

Type RM Length L Ch R = 1 ,4918.4  ,300.4,297.7,293.1
XS GIS Cut Line= 3
     1795342.262      227482.334     1795166.915      227313.931
     1795059.276      227032.681
#Sta/Elev= 30
       0 1284.03    48.6 1265.28   56.991262.266    68.1 1258.86    77.8 1257.17
   86.261255.086    87.5 1254.78    97.2 1251.43   126.4 1240.33   136.2 1236.84
   145.9 1234.53   155.6 1233.31   165.3 1232.58   204.2 1229.99  227.911228.543
   243.1 1227.67   330.6 1223.32     350 1222.55   408.3 1220.55     418 1220.39
   427.7  1220.5   437.4 1222.33   447.1 1226.32     486 1247.48   495.7 1252.36
   505.4  1256.9   515.1 1261.29   524.8  1265.5   534.6 1268.98   544.3 1271.17
#Mann= 6 ,-1 , 0
       0     .12       0   56.99    .016       0   86.26     .12       0
  227.91     .06       0   408.3    .045       0   427.7     .12       0
Bank Sta=408.3,427.7
XS Rating Curve= 0 ,0
Exp/Cntr=0.3,0.1

Type RM Length L Ch R = 1 ,4620.8  ,306.7,310.3,312
XS GIS Cut Line= 2
     1795533.234      227355.597     1795290.178      226926.778
#Sta/Elev= 30
       0 1294.35     9.7 1291.28    19.3 1287.82      29  1283.9    48.3 1275.21
   91.271254.522    96.6 1252.09   106.3 1248.75     116 1246.37   125.6 1243.08
  135.421238.042   154.6 1227.44   164.3  1223.6     174 1222.08   189.71221.473
   222.3 1220.53   270.6 1218.45   309.3 1217.75  331.111217.755   357.6 1217.45
   367.3 1217.01   378.1 1217.59   386.6 1218.96   405.9 1222.86   415.6 1225.26
   425.3 1228.81   434.9 1233.08   454.2 1242.41   473.6 1252.23   492.9 1262.44
#Mann= 7 ,-1 , 0
       0     .12       0   91.27    .016       0  135.42     .12       0
   189.7     .06       0  331.11     .12       0   357.6    .045       0
   378.1     .12       0
Bank Sta=357.6,378.1
XS Rating Curve= 0 ,0
Exp/Cntr=0.3,0.1

Type RM Length L Ch R = 1 ,4310.5  ,286.6,286.3,286
XS GIS Cut Line= 3
     1795774.553      227192.403     1795663.442      227017.056
     1795578.373       226827.82
#Sta/Elev= 30
       0  1294.5     9.4 1291.33    18.9 1288.33    28.3 1285.22    37.7 1281.34
    47.2  1276.8    75.5 1262.41   85.391257.262    94.4 1252.52   103.8 1249.45
   122.7 1245.05  129.361243.229   160.4 1234.61   169.8 1232.59  190.171229.414
   207.6  1226.8  226.471224.362   254.7 1221.22   292.5 1217.62   311.3 1215.07
   320.8 1214.23   330.2 1214.57   332.7 1215.09   339.6 1216.52     349 1219.28
   358.5 1221.83   367.9 1224.51   377.3 1228.21   386.8  1232.9   415.1 1248.68
#Mann= 7 ,-1 , 0
       0     .12       0   85.39    .016       0  129.36     .12       0
  190.17     .06       0  226.47     .12       0   311.3    .045       0
   332.7     .12       0
Bank Sta=311.3,332.7
XS Rating Curve= 0 ,0
Exp/Cntr=0.3,0.1

Type RM Length L Ch R = 1 ,4024.1  ,254.6,258.2,260.9
XS GIS Cut Line= 2
      1795995.04      227070.875     1795821.428      226692.403
#Sta/Elev= 30
       0 1294.55    19.4 1286.37      29 1282.08    38.7 1277.37    58.1 1267.39
    67.8 1262.62   71.141261.215    77.5 1258.54    87.2 1255.77    96.8 1254.26
   106.5  1251.8  110.751250.004   125.9 1243.26   154.9 1229.36   164.6 1224.98
   174.3 1221.53     184 1219.59  199.221219.003   222.7 1218.23   251.8 1216.93
   280.8 1215.44  311.681213.546  315.191213.282   319.6 1212.95   329.2 1212.64
   338.8  1213.8   348.6  1217.5     368 1228.37     397 1242.03   416.4 1250.67
#Mann= 7 ,-1 , 0
       0     .12       0   71.14    .016       0  110.75     .12       0
  199.22     .06       0  311.68     .12       0  315.19    .045       0
   338.8     .12       0
Bank Sta=315.19,338.8
XS Rating Curve= 0 ,0
Exp/Cntr=0.3,0.1

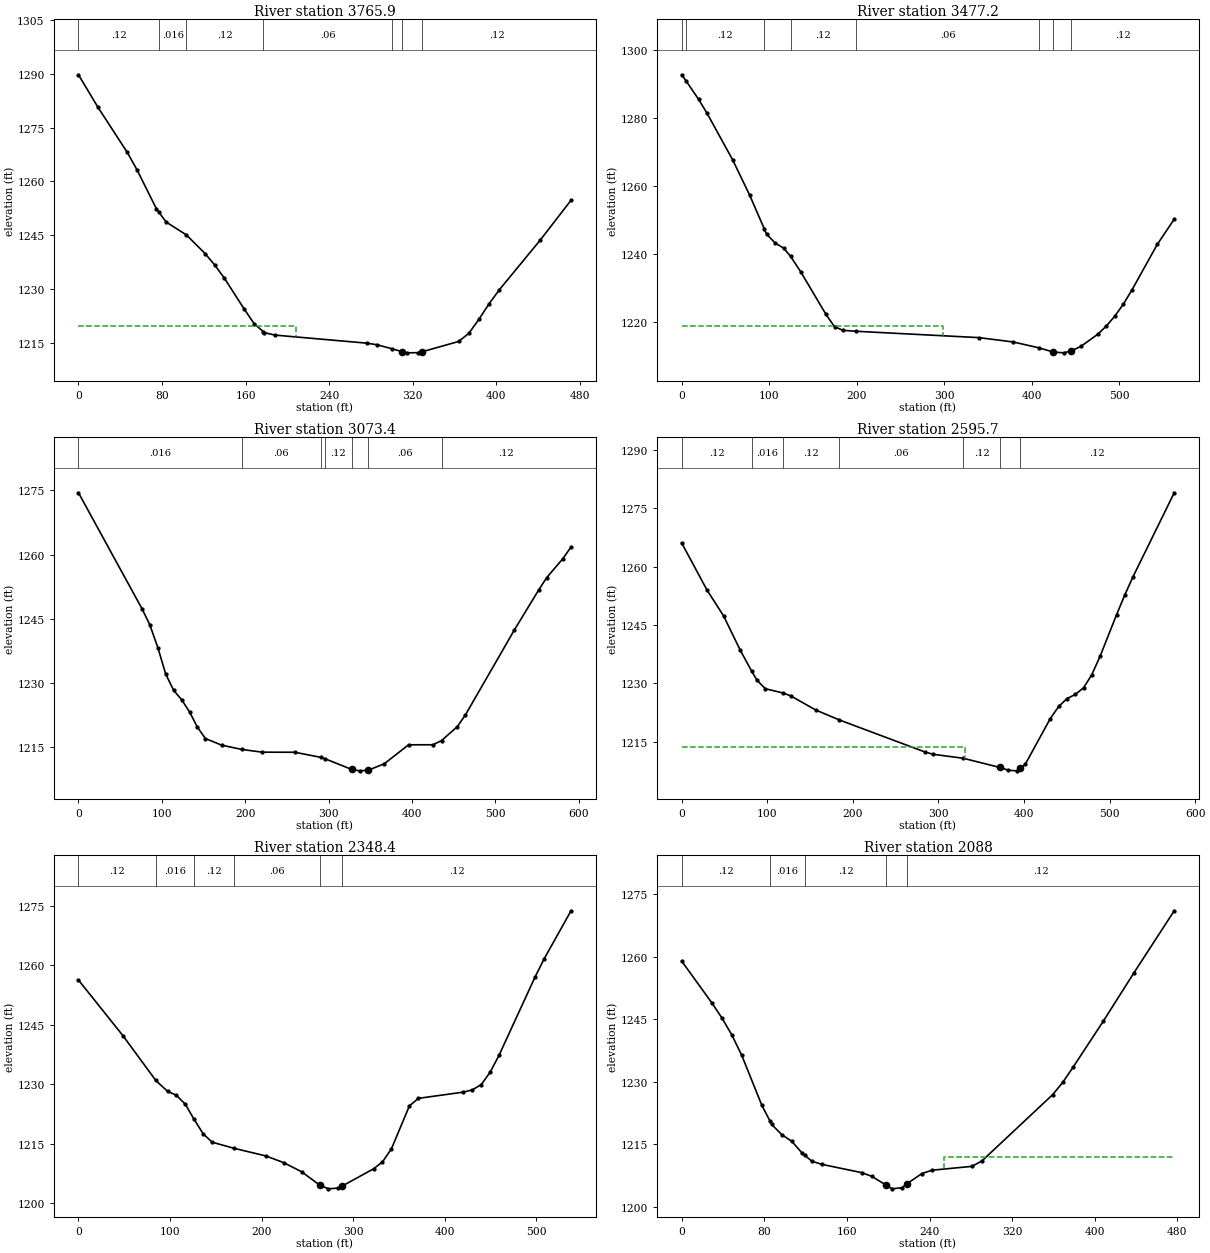
Type RM Length L Ch R = 1 ,3765.9  ,279.1,288.7,297.8
XS GIS Cut Line= 3
     1796165.178      227013.584     1796153.026      226855.597
     1796043.651      226562.195
#Sta/Elev= 30
       0  1289.7    18.6 1280.67    46.6 1268.14    55.9 1263.31    74.6  1252.4
   77.061251.421    83.9  1248.7  103.251245.116   121.2 1239.92   130.5 1236.71
   139.8 1233.01   158.4 1224.57   168.2 1220.38  176.871218.186     178  1217.9
   187.8 1217.21   275.9 1214.96   285.7 1214.52  300.331213.377   309.31212.633
     315 1212.26   324.8 1212.31   329.31212.581   363.9 1215.42   373.7 1217.67
   383.5 1221.64   393.3 1225.99   403.1 1229.88   442.2 1243.69   471.6 1254.76
#Mann= 7 ,-1 , 0
       0     .12       0   77.06    .016       0  103.25     .12       0
  176.87     .06       0  300.33     .12       0   309.3    .045       0
   329.3     .12       0
#XS Ineff= 2 , 0
          208.06 1219.68
Permanent Ineff=
       F       F
Bank Sta=309.3,329.3
XS Rating Curve= 0 ,0
Exp/Cntr=0.3,0.1

Type RM Length L Ch R = 1 ,3477.2  ,389.9,403.8,416.7
XS GIS Cut Line= 2
     1796324.901      227011.847     1796349.206      226449.347
#Sta/Elev= 30
       0 1292.64     5.11290.821    19.4  1285.4    29.1 1281.28    58.2 1267.68
    77.7 1257.28   94.681247.222    97.1 1245.79   106.8 1243.22   116.5  1241.7
  124.451239.307   135.9 1234.82     165  1222.2   174.7 1218.62   184.4 1217.54
  199.37 1217.27   339.8  1215.4   378.6 1214.14  408.091212.418   424.81211.164
   436.8 1210.93   444.81211.451   456.2 1212.81   475.7  1216.4   485.4 1218.81
   495.1 1221.72   504.8 1225.22   514.5 1229.32   543.6 1242.78     563 1250.21
#Mann= 8 ,-1 , 0
       0    .016       0     5.1     .12       0   94.68    .016       0
  124.45     .12       0  199.37     .06       0  408.09     .12       0
   424.8    .045       0   444.8     .12       0
#XS Ineff= 2 , 0
          298.62 1218.73
Permanent Ineff=
       F       F
Bank Sta=424.8,444.8
XS Rating Curve= 0 ,0
Exp/Cntr=0.3,0.1

Type RM Length L Ch R = 1 ,3073.4  ,477.7,477.7,474
XS GIS Cut Line= 4
      1796557.54      227017.056     1796576.637      226866.014
     1796739.831      226647.264     1796755.456      226482.334
#Sta/Elev= 30
       0 1274.45    76.1  1247.4    85.6 1243.59    95.2 1238.28   104.7 1232.06
   114.2 1228.31   123.7 1226.12   133.2 1223.29   142.7 1219.69   152.2 1217.06
   171.7 1215.51   195.91214.507   220.5 1213.87   259.5 1213.85   290.51212.667
   295.11212.378   327.7 1209.84   337.4 1209.51   347.2 1209.63   366.7 1211.15
   395.9 1215.59   425.2  1215.6  435.461216.577   454.4 1219.83   464.1 1222.57
   522.6 1242.34   551.8 1251.69   561.6 1254.63   581.1 1259.09   590.8 1261.78
#Mann= 7 ,-1 , 0
       0    .016       0   195.9     .06       0   290.5    .016       0
   295.1     .12       0   327.7    .045       0   347.2     .06       0
  435.46     .12       0
Bank Sta=327.7,347.2
XS Rating Curve= 0 ,0
Exp/Cntr=0.3,0.1

Type RM Length L Ch R = 1 ,2595.7  ,255.1,247.4,239.2
XS GIS Cut Line= 3
     1796819.692      227048.306     1797017.609      226643.792
      1797026.29      226518.792
#Sta/Elev= 30
       0 1266.07    29.4 1254.05      49 1247.32    68.5 1238.49   81.941233.069
    88.1 1230.75    97.9  1228.6  118.231227.521   127.3 1226.79   156.6 1223.14
  184.161220.587   283.9 1212.38   293.7 1211.76  329.171210.725     372 1208.36
   381.8 1207.66   391.6  1207.5   395.5 1208.15   401.4 1209.14   430.8 1220.94
   440.6 1224.04   450.3 1226.08     460 1227.13   469.6 1228.83   479.2 1232.18
   488.9 1236.91   508.2 1247.61   517.8 1252.69   527.4 1257.37   575.6 1278.97
#Mann= 7 ,-1 , 0
       0     .12       0   81.94    .016       0  118.23     .12       0
  184.16     .06       0  329.17     .12       0     372    .045       0
   395.5     .12       0
#XS Ineff= 2 , 0
          330.59 1213.68
Permanent Ineff=
       F       F
Bank Sta=372,395.5
XS Rating Curve= 0 ,0
Exp/Cntr=0.3,0.1

Type RM Length L Ch R = 1 ,2348.4  ,269.4,260.4,246.2
XS GIS Cut Line= 3
     1797250.248      227067.403     1797196.428      226900.736
     1797231.151      226539.625
#Sta/Elev= 30
       0  1256.3    48.6 1242.26   84.431230.981    97.3 1228.24     107 1227.23
   116.8 1224.95  125.781221.358   136.2 1217.51     146 1215.41   169.31213.907
   204.6 1211.95   224.2 1210.25   243.8 1207.94   263.4 1204.59     273 1203.65
     283 1203.84     288 1204.36   322.2 1208.69     332 1210.44   341.8 1213.76
   361.4 1224.57   371.2 1226.47   420.3 1228.04   430.1 1228.61   439.9 1229.95
   449.7 1233.12   459.5 1237.44   498.7 1257.12   508.5 1261.64   537.9 1273.77
#Mann= 6 ,-1 , 0
       0     .12       0   84.43    .016       0  125.78     .12       0
   169.3     .06       0   263.4    .045       0     288     .12       0
Bank Sta=263.4,288
XS Rating Curve= 0 ,0
Exp/Cntr=0.3,0.1

Type RM Length L Ch R = 1 ,2088    ,432.9,439,440.7
XS GIS Cut Line= 3
     1797501.984      227004.903     1797406.498      226709.764
     1797406.498      226543.097
#Sta/Elev= 30
       0 1258.98    29.1 1248.98    38.8 1245.38    48.5 1241.28    58.2 1236.32
    77.6 1224.36   85.561220.538    87.2 1219.75    96.9 1217.31   106.6  1215.7
   116.3 1212.96  119.291212.334     126 1210.93   135.7 1210.17   174.5 1208.17
   184.2 1207.28     198 1205.17   203.6 1204.29   213.3 1204.56     218  1205.5
   232.6 1207.96   242.3 1208.76   281.1 1209.69   290.8 1211.01   359.2  1226.9
     369 1229.87   378.8 1233.43   408.2 1244.53   437.6 1256.04   476.9 1271.05
#Mann= 5 ,-1 , 0
       0     .12       0   85.56    .016       0  119.29     .12       0
     198    .045       0     218     .12       0
#XS Ineff= 2 , 0
                          254.11         1211.87
Permanent Ineff=
       F       F
Bank Sta=198,218
XS Rating Curve= 0 ,0
Exp/Cntr=0.3,0.1