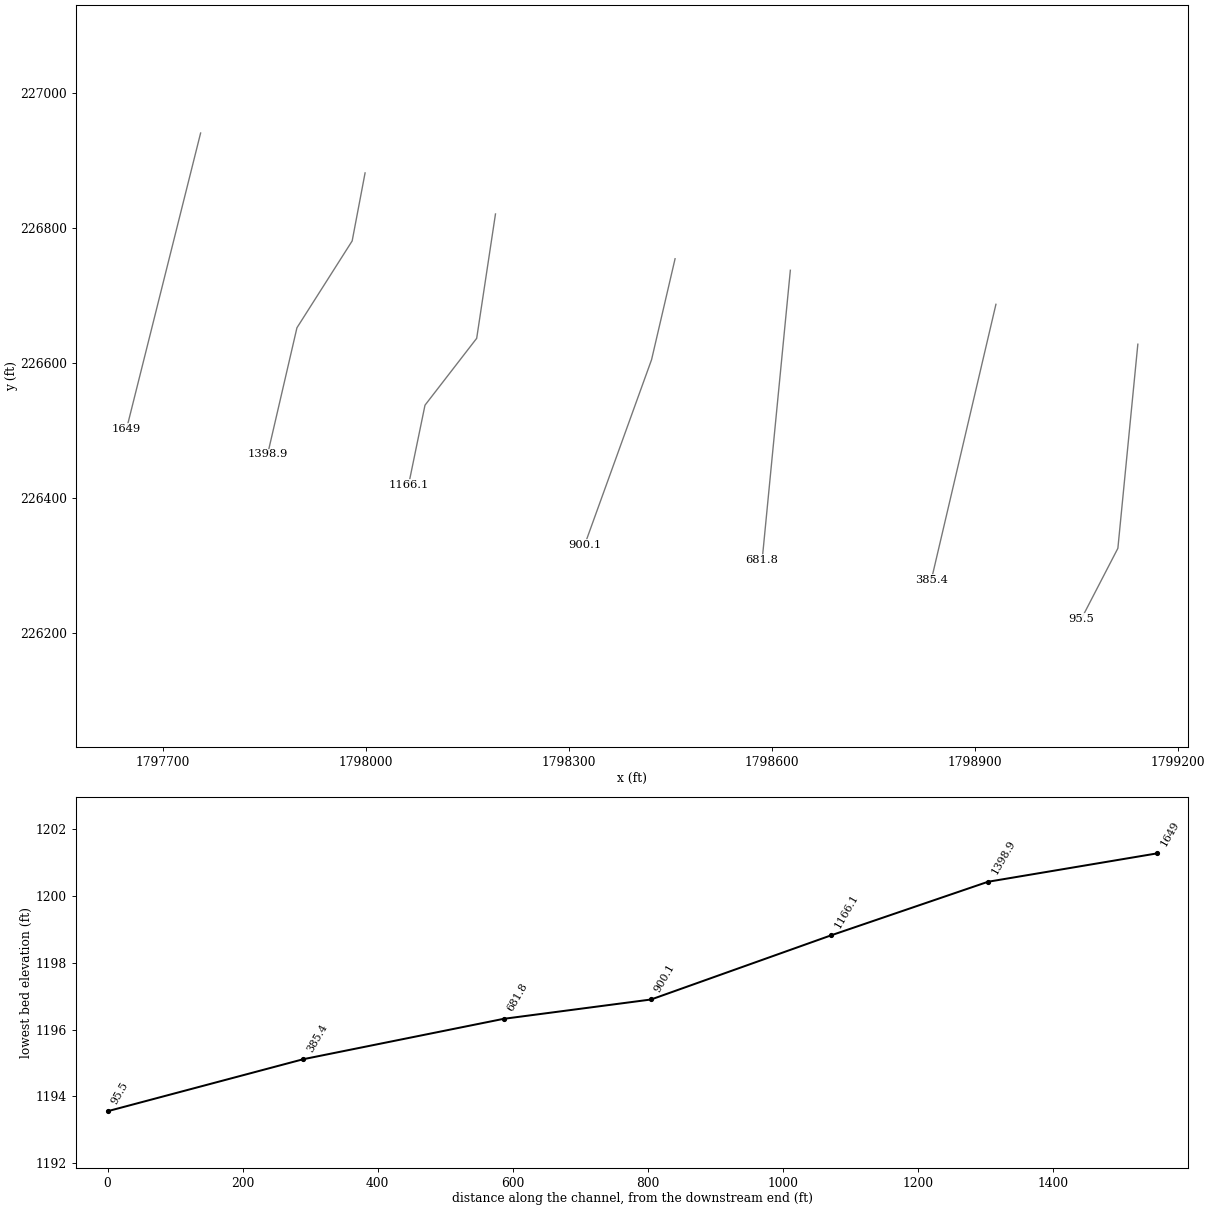
HEC-RAS study INDIANFKCK.prj: INDIANFKCK

--- INDIANFKCK.g01 (geometry) --- (continued)

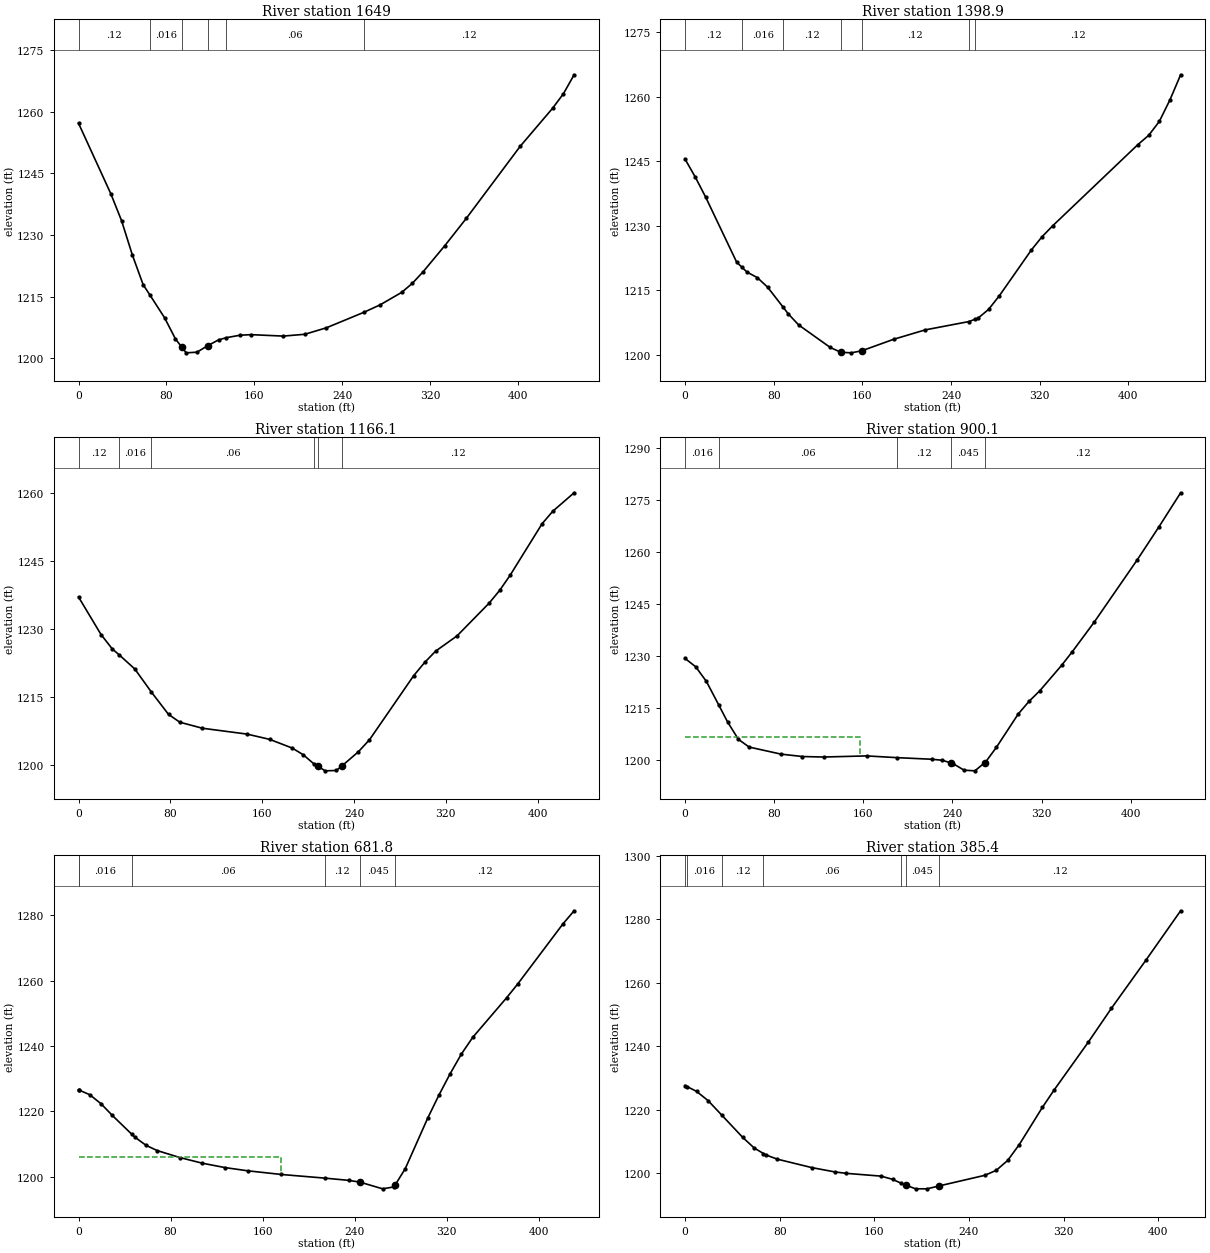
Type RM Length L Ch R = 1 ,1649    ,257.1,250,242.5
XS GIS Cut Line= 2
     1797755.456      226940.667     1797646.081      226503.167
#Sta/Elev= 30
       0  1257.2    29.4 1240.03    39.2 1233.45      49 1225.12    58.8 1217.89
   64.891215.398    78.4 1209.79    88.2 1204.67   94.061202.643      98 1201.28
   107.8 1201.44   117.6 1203.03   127.4 1204.43  134.59 1204.98     147 1205.57
   156.9 1205.71   186.3 1205.36   205.9  1205.8   225.5 1207.37  259.641211.147
   274.5 1212.97   294.1 1216.01   303.9 1218.23   313.7 1221.06   333.3 1227.37
   352.9 1234.03     402  1251.6   431.4 1260.84   441.2 1264.35     451    1269
#Mann= 6 ,-1 , 0
       0     .12       0   64.89    .016       0   94.06    .045       0
   117.6     .12       0  134.59     .06       0  259.64     .12       0
Bank Sta=94.06,117.6
XS Rating Curve= 0 ,0
Exp/Cntr=0.3,0.1

Type RM Length L Ch R = 1 ,1398.9  ,234.8,232.8,230.4
XS GIS Cut Line= 4
     1797998.512      226881.639     1797979.415      226780.945
     1797897.817      226652.472     1797854.415      226464.972
#Sta/Elev= 30
       0 1245.45     9.3 1241.25    18.6 1236.62    46.6 1221.49   51.461220.293
    55.9  1219.2    65.2 1217.91    74.5 1215.69   88.65 1210.99    93.2 1209.46
   102.5 1206.91     131 1201.68   140.5 1200.56     150 1200.43   159.6 1200.92
   188.1 1203.57   216.6 1205.76  255.981207.691  261.531208.217   264.3 1208.48
   273.9 1210.54   283.6 1213.71   312.4 1224.32     322 1227.39   331.7 1229.96
   408.6 1248.84   418.3 1250.98   427.9 1254.22   437.5 1259.24   447.1 1265.05
#Mann= 7 ,-1 , 0
       0     .12       0   51.46    .016       0   88.65     .12       0
   140.5    .045       0   159.6     .12       0  255.98     .06       0
  261.53     .12       0
Bank Sta=140.5,159.6
XS Rating Curve= 0 ,0
Exp/Cntr=0.3,0.1

Type RM Length L Ch R = 1 ,1166.1  ,258.3,266,272.5
XS GIS Cut Line= 4
      1798191.22      226820.875     1798163.442      226636.847
     1798087.053      226537.889     1798062.748      226419.834
#Sta/Elev= 30
       0 1237.17    19.6 1228.89    29.4 1225.71   35.161224.458      49  1221.3
   63.521216.183    78.4 1211.27    88.2 1209.55   107.8 1208.22   146.9 1206.92
   166.5 1205.76   186.1 1203.85   195.7 1202.38  205.221200.319   208.6 1199.79
     215 1198.82   224.6  1198.9  229.431199.896   243.8 1203.03   253.4 1205.65
   291.9 1219.79   301.5 1222.72   311.1 1225.23   329.7 1228.58   357.5 1235.76
   366.8  1238.6     376 1241.97   403.8 1253.32   413.1 1256.07   431.7 1260.15
#Mann= 6 ,-1 , 0
       0     .12       0   35.16    .016       0   63.52     .06       0
  205.22     .12       0   208.6    .045       0  229.43     .12       0
Bank Sta=208.6,229.43
XS Rating Curve= 0 ,0
Exp/Cntr=0.3,0.1

Type RM Length L Ch R = 1 ,900.1   ,212.7,218.3,224
XS GIS Cut Line= 3
     1798456.629      226754.594     1798421.907      226605.288
     1798322.949      226330.983
#Sta/Elev= 30
       0 1229.27     9.6 1226.86    19.2 1222.64   30.071215.978    38.3 1210.92
    47.9 1205.98    57.5 1203.75    86.2 1201.71   105.4 1201.02   124.6 1200.88
     163  1201.2  190.461200.697   221.3 1200.24     231 1199.95   238.91199.136
   240.8 1198.94   250.5 1197.09   260.2  1196.9   268.91199.205   269.9 1199.47
   279.6 1203.71   299.1 1213.27   308.8 1216.91   318.5 1219.97     338 1227.26
   347.7 1231.23   367.1 1239.63     406 1257.69   425.5 1267.21   444.9 1276.98
#Mann= 5 ,-1 , 0
       0    .016       0   30.07     .06       0  190.46     .12       0
   238.9    .045       0   268.9     .12       0
#XS Ineff= 2 , 0
          157.07 1206.77
Permanent Ineff=
       F       F
Bank Sta=238.9,268.9
XS Rating Curve= 0 ,0
Exp/Cntr=0.3,0.1

Type RM Length L Ch R = 1 ,681.8   ,299.2,296.4,292.9
XS GIS Cut Line= 2
     1798626.984      226737.542     1798585.317      226308.722
#Sta/Elev= 30
       0 1226.63     .771226.512     9.8 1225.13    19.6 1222.36    29.4 1218.79
   46.08 1213.11      49 1212.13    58.8 1209.62    68.5 1208.02    88.1  1205.9
   107.7 1204.16   127.3 1202.83   146.9 1201.85   176.2 1200.72  213.961199.606
     235 1198.91   244.8 1198.36   264.4 1196.32   274.2 1196.92   275.3 1197.54
     284 1202.48   303.6 1218.01   313.3 1225.01   323.1  1231.6   332.9 1237.63
   342.7  1242.7   372.1  1254.8   381.9 1259.08     421 1277.38   430.8 1281.44
#Mann= 6 ,-1 , 0
       0     .12       0     .77    .016       0   46.08     .06       0
  213.96     .12       0   244.8    .045       0   275.3     .12       0
#XS Ineff= 2 , 0
          175.99 1205.94
Permanent Ineff=
       F       F
Bank Sta=244.8,275.3
XS Rating Curve= 0 ,0
Exp/Cntr=0.3,0.1

Type RM Length L Ch R = 1 ,385.4   ,286.9,289.8,291.8
XS GIS Cut Line= 2
     1798930.803      226687.195     1798835.317      226279.209
#Sta/Elev= 30
       0 1227.61     1.81227.272     9.7 1225.79    19.5 1222.87   30.871218.378
    48.7 1211.32    58.5 1207.95   66.311206.219    68.2  1205.8      78 1204.45
   107.2 1201.79   126.7 1200.43   136.4 1199.98   165.7 1199.11   175.4 1198.11
  182.381196.923   186.6 1196.26   194.9 1195.13   204.6 1195.11   214.4 1195.99
   253.4 1199.36   263.1 1200.93   272.8 1204.06   282.6 1209.05   302.1 1220.73
   311.8 1226.09   341.1 1241.36   360.5 1251.94   389.8 1267.15     419 1282.61
#Mann= 7 ,-1 , 0
       0     .12       0     1.8    .016       0   30.87     .12       0
   66.31     .06       0  182.38     .12       0   186.6    .045       0
   214.4     .12       0
Bank Sta=186.6,214.4
XS Rating Curve= 0 ,0
Exp/Cntr=0.3,0.1

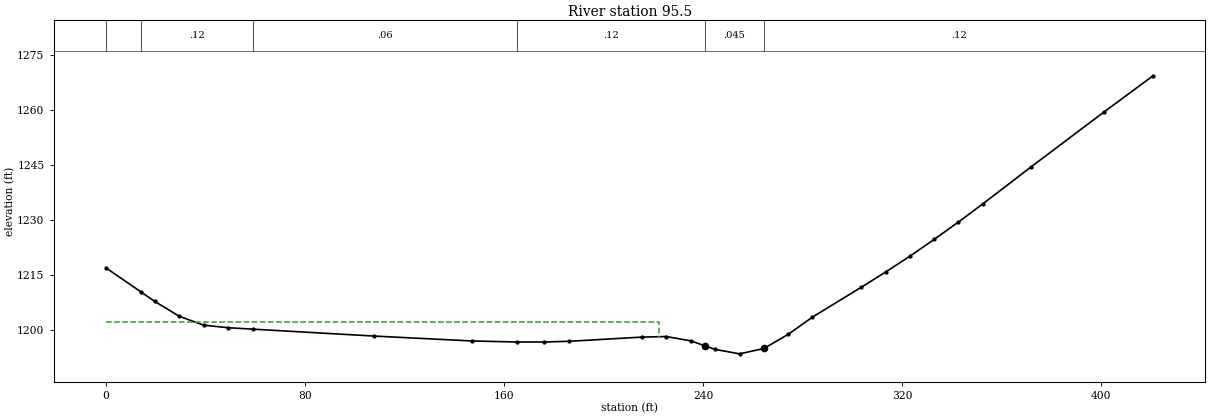
Type RM Length L Ch R = 1 ,95.5    ,76.7,95.5,114.2
XS GIS Cut Line= 3
     1799140.526      226628.167     1799111.012      226326.084
     1799057.192      226221.917
#Sta/Elev= 30
       0 1216.93    13.9 1210.47    19.6  1207.8    29.4 1203.79    39.2 1201.36
      49 1200.66   59.061200.269   107.7 1198.39   146.9 1197.06  165.141196.772
   176.2 1196.78     186 1196.96   215.4 1198.11   225.2 1198.26     235 1197.08
  240.741195.721   244.8 1194.76   254.6 1193.55   264.4 1195.01   274.2 1198.87
   283.9 1203.55   303.5 1211.66   313.3 1215.82   323.1 1220.15   332.8 1224.69
   342.6 1229.44   352.4 1234.39   371.9 1244.51   401.2 1259.45   420.8 1269.25
#Mann= 6 ,-1 , 0
       0    .016       0    13.9     .12       0   59.06     .06       0
  165.14     .12       0  240.74    .045       0   264.4     .12       0
#XS Ineff= 2 , 0
          222.04 1202.26
Permanent Ineff=
       F       F
Bank Sta=240.74,264.4
XS Rating Curve= 0 ,0
Exp/Cntr=0.3,0.1
LCMann Table=0

Chan Stop Cuts=-1
Use User Specified Reach Order=0
Composite Channel Slope=5